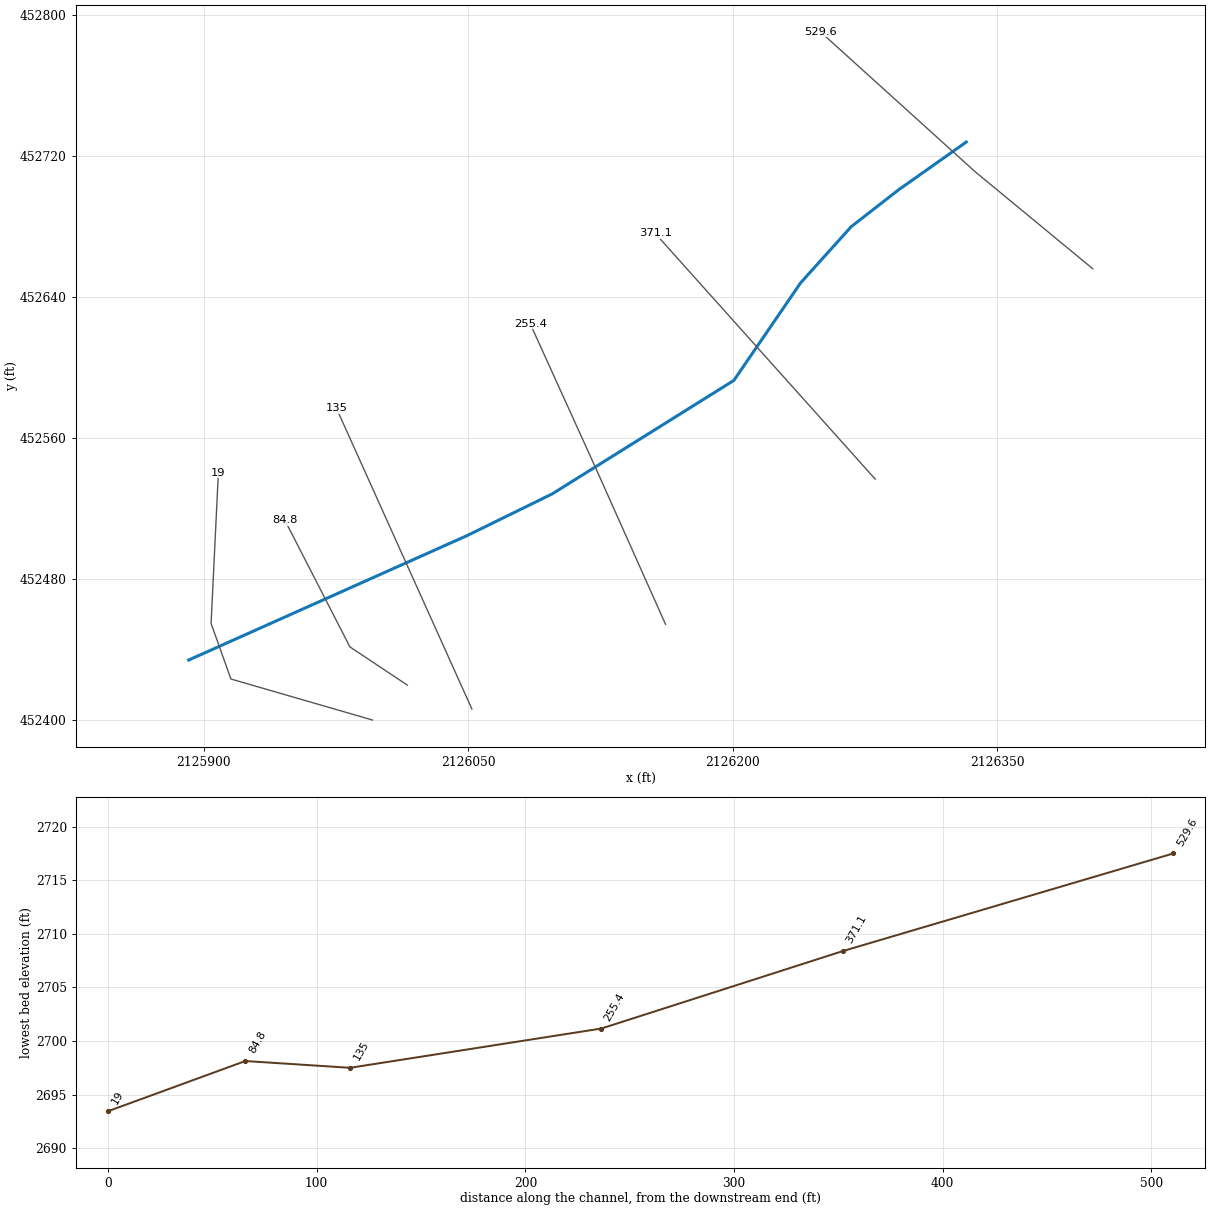
--- CoatsRun.prj (project) ---

Proj Title=CoatsRun
Current Plan=p01
Default Exp/Contr=0,0
English Units
Geom File=g01
Flow File=f01
Plan File=p01
BEGIN DESCRIPTION:
END DESCRIPTION:
DSS Export Rating Curves= 0
DSS Export Rating Curve Sorted= 0
DSS Export Volume Flow Curves= 0
DXF OffsetX= 0
DXF OffsetY= 0
DXF ScaleX= 0
DXF ScaleY= 0

--- CoatsRun.p01 (plan) ---

Plan Title=Floodplain
Program Version=4.00
Geom File=g01
Flow File=f01
K Sum by GR=0
Std Step Tol=0.01
Critical Tol=0.01
Num of Std Step Trials=20
Max Error Tol=0.3
Flow Tol Ratio=0.001
Split Flow NTrial=30
Split Flow Tol=0.02
Split Flow Ratio=0.02
Log Output Level=0
Friction Slope Method=1
Unsteady Friction Slope Method=2
Unsteady Bridges Friction Slope Method=1
Global Log Level=0
CheckData=False
Run HTab=0
Run UNet=0
Run PostProcess=0
UNET Theta=0
UNET Theta Warmup=0
UNET ZTol=0
UNET ZSATol=0
UNET MxIter=0
UNET MaxInSteps=0
UNET DtIC=0
UNET DtMin=0
UNET MaxCRTS=0
UNET WFStab=0
UNET SFStab=0
UNET WFX=0
UNET SFX=0
UNET DSS MLevel=0
UNET DZMax Abort=0
UNET Convert EG Bridges=0
UNET Use Existing IB Tables=0
UNET Froude Limit=0
UNET Froude Power=0
Write IC File=0
Echo Input=False
Echo Output=False
Write Detailed=0

--- CoatsRun.f01 (steady flow) ---

Flow Title=NFF Regression Equation
Program Version=4.00
Number of Profiles=1
Profile Names=P100yr
River Rch & RM=CoatsRun,Main      ,529.6
519.1744
Boundary for River Rch & Prof#=CoatsRun,Main      ,1
Up Type=0
Dn Type=3
Dn Slope=0.029677

--- CoatsRun.g01 (geometry) ---

Geom Title=USGS 10m DEM
Program Version=4.00

River Reach=CoatsRun     ,Main
Reach XY= 8
     2126332.377      452727.823     2126294.139      452700.831
     2126267.147      452679.837     2126238.432      452647.954
     2126200.617      452592.686     2126097.697      452528.382
     2126049.358      452504.694     2125891.554      452434.155

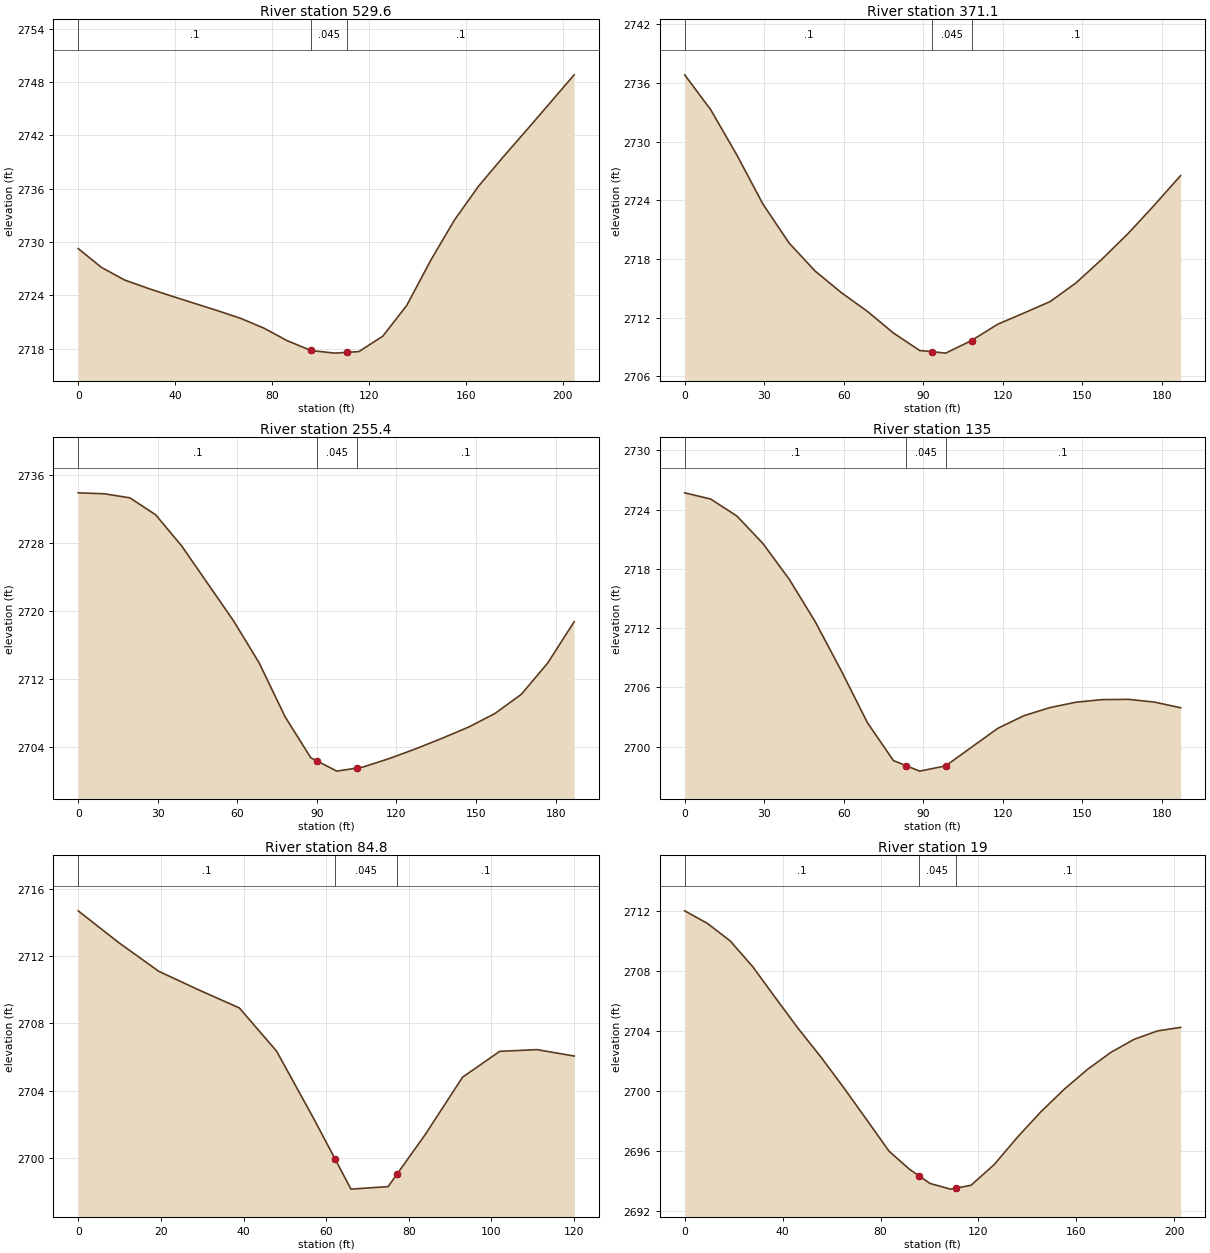
Type RM Length L Ch R = 1 ,529.6,161.3,158.5,155.9
XS GIS Cut Line= 3
     2126404.091      452655.986     2126337.492      452710.910
     2126249.633      452790.368
#Sta/Elev= 24
       0 2729.26     9.6 2727.14    19.2 2725.72    28.8 2724.79    38.4 2723.93
    48.0 2723.10    57.6 2722.27    67.1 2721.41    76.7 2720.31    86.3 2718.90
      96 2717.81    96.2 2717.79   106.1 2717.50     111 2717.59   115.9 2717.67
   125.8 2719.41   135.7 2722.88   145.6 2727.95   155.4 2732.48   165.3 2736.27
   175.2 2739.47   185.0 2742.53   194.9 2745.66   204.8 2748.80
#Mann= 3 , 0 , 0
       0     0.1       0      96   0.045       0     111     0.1       0
Bank Sta=      96,     111
Exp/Cntr=0.3,0.1

Type RM Length L Ch R = 1 ,371.1,122.7,115.7,108.8
XS GIS Cut Line= 2
     2126280.762      452536.712     2126156.060      452676.006
#Sta/Elev= 22
       0 2736.85     9.8 2733.29    19.7 2728.64    29.5 2723.64    39.4 2719.64
    49.2 2716.78    59.0 2714.59    68.9 2712.66    78.7 2710.45    88.6 2708.66
    93.2 2708.54    98.4 2708.39   108.2 2709.68   108.2 2709.69   118.1 2711.35
   127.9 2712.49   137.8 2713.66   147.6 2715.58   157.4 2718.01   167.3 2720.65
   177.1 2723.52   187.0 2726.55
#Mann= 3 , 0 , 0
       0     0.1       0    93.2   0.045       0   108.2     0.1       0
Bank Sta=    93.2,   108.2
Exp/Cntr=0.3,0.1

Type RM Length L Ch R = 1 ,255.4,120.3,120.4,120.3
XS GIS Cut Line= 3
     2126161.889      452454.439     2126122.113      452543.424
     2126085.120      452624.909
#Sta/Elev= 22
       0 2733.90     9.8 2733.79    19.5 2733.31    29.2 2731.32    39.0 2727.66
    48.7 2723.29    58.5 2718.88    68.2 2713.92    78.0 2707.57    87.7 2702.74
    90.2 2702.34    97.5 2701.17   105.2 2701.54   107.4 2701.65   117.4 2702.66
   127.3 2703.80   137.2 2705.03   147.2 2706.35   157.1 2707.94   167.1 2710.21
   177.0 2713.87   187.0 2718.74
#Mann= 3 , 0 , 0
       0     0.1       0    90.2   0.045       0   105.2     0.1       0
Bank Sta=    90.2,   105.2
Exp/Cntr=0.3,0.1

Type RM Length L Ch R = 1 ,135,49,50.2,51.3
XS GIS Cut Line= 2
     2126052.106      452406.408     2125975.337      452576.877
#Sta/Elev= 21
       0 2725.69     9.8 2725.06    19.7 2723.34    29.5 2720.56    39.4 2716.95
    49.2 2712.65    59.0 2707.70    68.9 2702.42    78.7 2698.58    83.4 2698.07
    88.6 2697.51    98.4 2698.04   108.2 2699.94   118.1 2701.85   127.9 2703.12
   137.8 2703.95   147.6 2704.49   157.4 2704.75   167.3 2704.78   177.1 2704.50
   187.0 2703.93
#Mann= 3 , 0 , 0
       0     0.1       0    83.4   0.045       0    98.4     0.1       0
Bank Sta=    83.4,    98.4
Exp/Cntr=0.3,0.1

Type RM Length L Ch R = 1 ,84.8,65.1,65.8,59.1
XS GIS Cut Line= 3
     2126015.476      452419.974     2125982.971      452441.600
     2125946.005      452513.572
#Sta/Elev= 16
       0 2714.70     9.8 2712.81    19.5 2711.10    29.3 2709.98    39.0 2708.92
    48.0 2706.35    57.0 2702.33    62.1 2699.96    66.0 2698.14    75.0 2698.29
    77.1 2699.02    84.0 2701.40    93.0 2704.80   102.0 2706.34   111.0 2706.44
   120.0 2706.06
#Mann= 3 , 0 , 0
       0     0.1       0    62.1   0.045       0    77.1     0.1       0
Bank Sta=    62.1,    77.1
Exp/Cntr=0.3,0.1

Type RM Length L Ch R = 1 ,19,20.9,19,24.5
XS GIS Cut Line= 4
     2125995.727      452400.170     2125915.500      452423.413
     2125904.254      452454.903     2125908.394      452540.468
#Sta/Elev= 25
       0 2712.04     9.3 2711.20    18.6 2710.03    27.8 2708.31    37.1 2706.23
    46.4 2704.18    55.7 2702.27    65.0 2700.23    74.2 2698.13    83.5 2695.99
    91.9 2694.78    95.7 2694.35   100.2 2693.84   108.6 2693.46   110.7 2693.52
   117.0 2693.72   126.5 2695.11   136.0 2696.94   145.5 2698.62   155.0 2700.12
   164.6 2701.46   174.1 2702.59   183.6 2703.46   193.1 2704.02   202.6 2704.26
#Mann= 3 , 0 , 0
       0     0.1       0    95.7   0.045       0   110.7     0.1       0
Bank Sta=    95.7,   110.7
Exp/Cntr=0.3,0.1